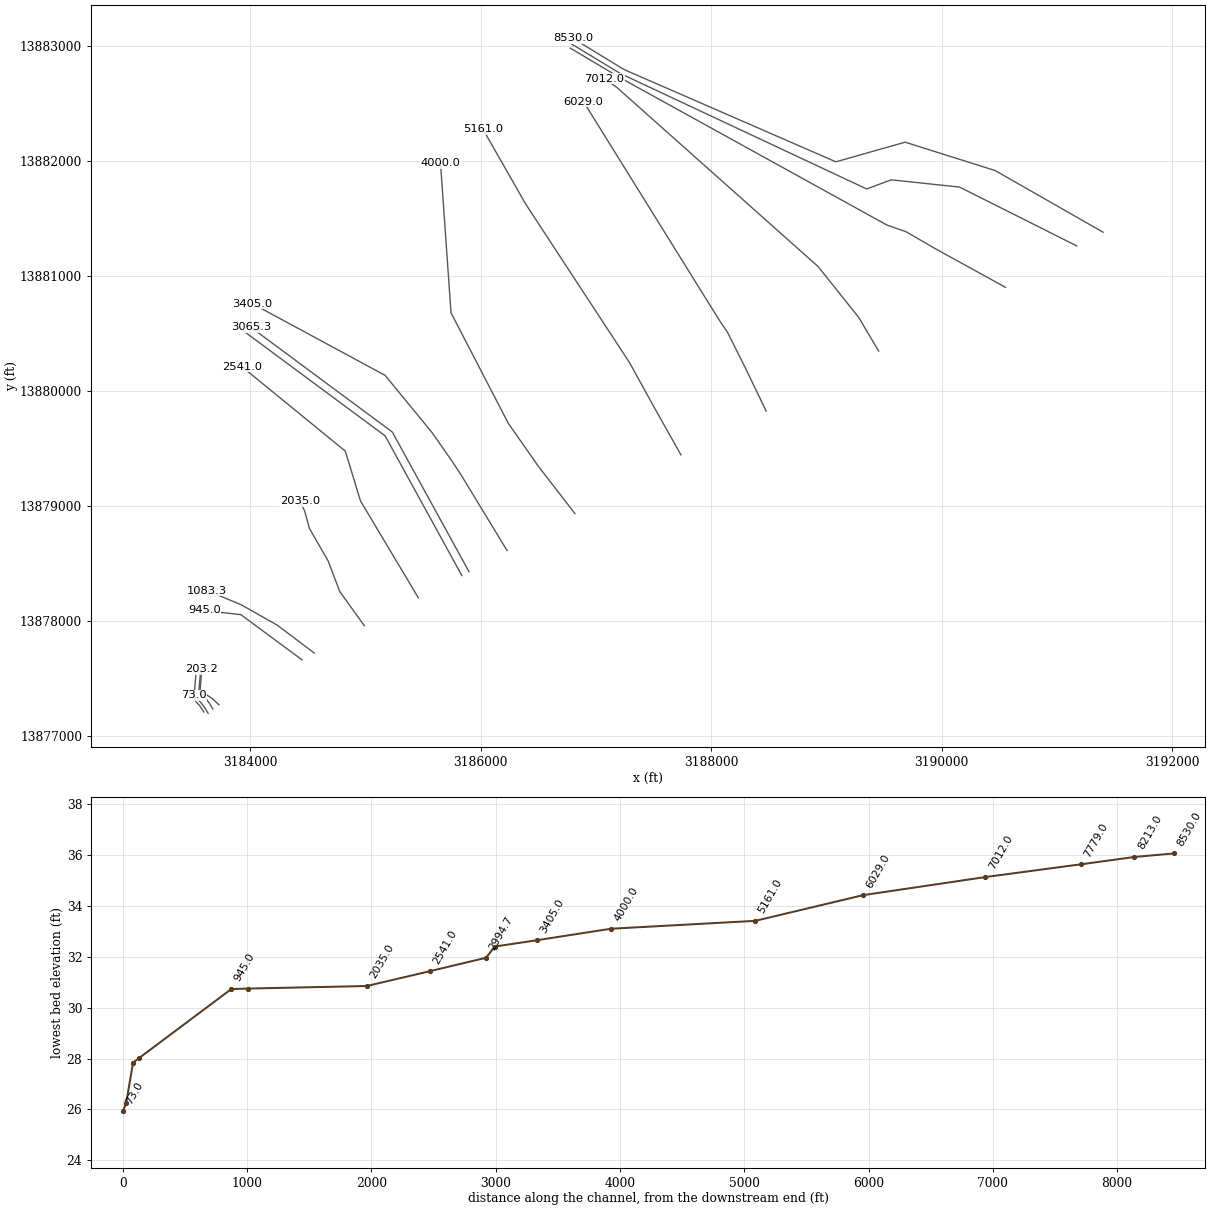
--- N117-00-00.PRJ (project) ---

Proj Title=N117-00-00
Current Plan=p02
Default Exp/Contr=.3,.1
English Units
Geom File=g01
Flow File=f02
Flow File=f01
Plan File=p01
Plan File=p02
Y Axis Title=Elevation
X Axis Title(PF)=Main Channel Distance
X Axis Title(XS)=Station
BEGIN DESCRIPTION:
Carpenters Bayou Watershed
Tributary 11.715 to Carpenters Bayou
HCFCD Unit N117-00-00
Flood Hazard Model
10, 2, 1, 0.2% Event
Filename N117-00-00.prj
Prepared by:  Watershed Concepts  Date: 07/11/02
Reviewed by:                      Date:
STATUS FINAL
END DESCRIPTION:
DSS Export Rating Curves= 0
DSS Export Rating Curve Sorted= 0
DSS Export Volume Flow Curves= 0
DXF OffsetX= 0
DXF OffsetY= 0
DXF ScaleX= 1
DXF ScaleY= 10

--- N117-00-00.p02 (plan) ---

Plan Title=Floodway
Version=Version 3.0.1  Mar 2001
Short Identifier=Floodway0607
Geom File=g01
Flow File=f02
Subcritical Flow
K Sum by GR= 0
Std Step Tol= 0.01
Critical Tol= 0.01
Num of Std Step Trials= 20
Max Error Tol= 0.3
Flow Tol Ratio= 0.001
Split Flow NTrial= 30
Split Flow Tol= 0.02
Split Flow Ratio= 0.02
Log Output Level= 0
Friction Slope Method= 1
Unsteady Friction Slope Method= 2
Parabolic Critical Depth
Global Vel Dist= 0 , 0 , 0
Global Log Level= 0
CheckData=True
Encroach Param=-1 ,0,0, 2
Encroach River=N117-00-00
Encroach Reach=Reach - 1
Encroach Node=8530.0
       1    4950    5022
Encroach Node=8213.0
       1    4800    5022
Encroach Node=7779.0
       1    4900    5038
Encroach Node=7012.0
       1    4750    5032
Encroach Node=6029.0
       1    4750    5030
Encroach Node=5161.0
       1    4750    5045
Encroach Node=4000.0
       1    4750    5040
Encroach Node=3405.0
       1    4720    5050
Encroach Node=3065.3
       1    4720    5100
Encroach Node=3030.0
       1    4700    5100
Encroach Node=2994.7
       1    4700    5100
Encroach Node=2541.0
       1    4700    5100
Encroach Node=2035.0
       1    4700    5075
Encroach Node=1083.3
       1    4700    5075
Encroach Node=945.0
       1    4700    5075
Encroach Node=203.2
       1    4940    5075
Encroach Node=154.4
       1    4975    5050
Encroach Node=126.6
       1    4975    5030
Encroach Node=98.8
       1  4977.8    5017
Encroach Node=73.0
       1  4978.2  5050.5
Encroach Reach=N117-00-00_0001
Encroach Node=8530.0
       1    4950    5022
Encroach Node=8213.0
       1    4800    5022
Encroach Node=7779.0
       1    4900    5038
Encroach Node=7012.0
       1    4750    5032
Encroach Node=6029.0
       1    4750    5030
Encroach Node=5161.0
       1    4750    5045
Encroach Node=4000.0
       1    4750    5040
Encroach Node=3405.0
       1    4720    5050
Encroach Node=3065.3
       1    4720    5100
Encroach Node=3030.0
       1    4700    5100
Encroach Node=2994.7
       1    4700    5100
Encroach Node=2541.0
       1    4700    5100
Encroach Node=2035.0
       1    4700    5075
Encroach Node=1083.3
       1    4700    5075
Encroach Node=945.0
       1    4700    5075
Encroach Node=203.2
       1    4940    5075
Encroach Node=154.4
       1    4975    5050
Encroach Node=126.6
       1    4975    5030
Encroach Node=98.8
       1  4977.8    5017
Encroach Node=73.0
       1  4978.2  5050.5
Computation Interval=1HOUR
Output Interval=1HOUR
Run HTab= 0
Run UNet= 0
Run PostProcess= 0
UNET Theta= 1
UNET ZTol= 0.02
UNET ZSATol= 0.1
UNET MxIter= 20
UNET MaxInSteps= 20
UNET DtIC= 0
UNET DtMin= 0
UNET MaxCRTS= 20
UNET WFStab= 2
UNET SFStab= 1
UNET WFX= 1
UNET SFX= 1
UNET Convert EG Bridges=-1
UNET Use Existing IB Tables=-1
Instantaneous Interval=1HOUR
Write IC File= 0
IC Time=0
Write Velocity= 0
Write Detailed= 0

--- N117-00-00.p01 (plan) ---

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Plan Title=FEMA Effective June 2007
Short Identifier=FEMAeff0607
Geom File=g01
Flow File=f01

--- N117-00-00.f02 (steady flow) ---

Flow Title=Floodway
Program Version=3.13
Number of Profiles= 2
Profile Names=1PCT_100yr, 1PCTFloodway_100yrFW
River Rch & RM=N117-00-00,N117-00-00_0001 ,8530
     165     165
River Rch & RM=N117-00-00,N117-00-00_0001 ,6029
     189     189
River Rch & RM=N117-00-00,N117-00-00_0001 ,4000
     546     546
River Rch & RM=N117-00-00,N117-00-00_0001 ,3405
     587     587
River Rch & RM=N117-00-00,N117-00-00_0001 ,2035
     968     968
River Rch & RM=N117-00-00,N117-00-00_0001 ,1083.3
     984     984
River Rch & RM=N117-00-00,N117-00-00_0001 ,945.0
    1025    1025
Boundary for River Rch & Prof#=N117-00-00,N117-00-00_0001 , 1
Up Type= 0
Dn Type= 3
Dn Slope=0.0016
Boundary for River Rch & Prof#=N117-00-00,N117-00-00_0001 , 2
Up Type= 0
Dn Type= 3
Dn Slope=0.0016
DSS Import GetInterval= 0
DSS Import GetPeak= 0
DSS Import FillOption= 0

--- N117-00-00.f01 (steady flow) ---

Flow Title=FEMA Effective June 2007
Number of Profiles= 4
Profile Names=10PCT_10yr, 2PCT_50yr, 1PCT_100yr, 0.2PCT_500yr
River Rch & RM=N117-00-00,N117-00-00_0001,8530
      89     139     165     244
River Rch & RM=N117-00-00,N117-00-00_0001,6029
     101     159     189     278
River Rch & RM=N117-00-00,N117-00-00_0001,4000
     293     459     546     805
River Rch & RM=N117-00-00,N117-00-00_0001,3405
     315     493     587     866
River Rch & RM=N117-00-00,N117-00-00_0001,2035
     520     814     968    1427
River Rch & RM=N117-00-00,N117-00-00_0001,1083.3
     529     827     984    1450
River Rch & RM=N117-00-00,N117-00-00_0001,945.0
     551     861    1025    1511
Boundary for River Rch & Prof#=N117-00-00,N117-00-00_0001, 1
Up Type= 0
Dn Type= 3
Dn Slope= 0.00160
Boundary for River Rch & Prof#=N117-00-00,N117-00-00_0001, 2
Up Type= 0
Dn Type= 3
Dn Slope= 0.00160
Boundary for River Rch & Prof#=N117-00-00,N117-00-00_0001, 3
Up Type= 0
Dn Type= 3
Dn Slope= 0.00160
Boundary for River Rch & Prof#=N117-00-00,N117-00-00_0001, 4
Up Type= 0
Dn Type= 3
Dn Slope= 0.00160

--- N117-00-00.g01 (geometry) ---

Geom Title=N117-00-00 June 2007

River Reach=N117-00-00,N117-00-00_0001
Reach XY= 27
      3189264.94     13882063.23       3189385.5        13881839
       3189521.5        13881603         3189537        13881565
      3189552.75        13881538      3189572.75        13881517
      3189592.25        13881502      3189608.25        13881485
         3189616        13881463       3189619.5        13881441
         3189621        13881420      3189617.75        13881396
       3189610.5        13881373       3189597.5        13881355
      3189580.75        13881341       3189562.5        13881327
       3186238.5        13879560         3183750        13878206
         3183750        13878206       3183728.5     13878018.75
      3183680.21     13877616.29      3183675.38     13877532.58
      3183651.63     13877374.78      3183644.79     13877310.43
      3183628.69     13877283.06      3183610.98     13877266.96
      3183569.13     13877247.64      3183553.03     13877231.54

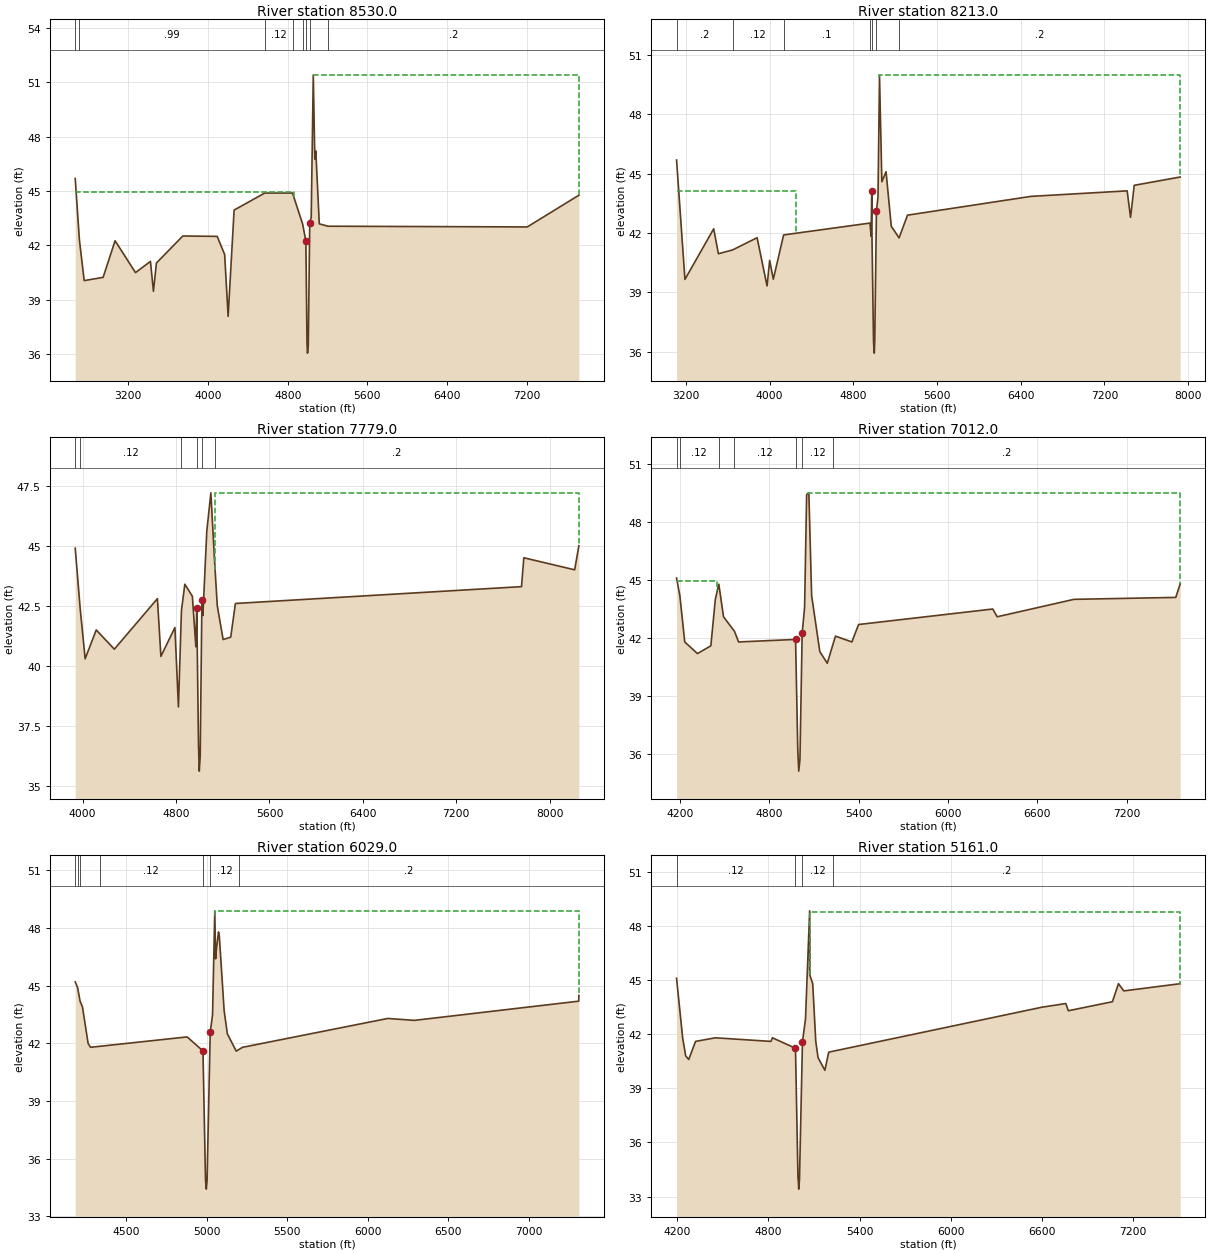
Type RM Length L Ch R = 1 ,8530.0,371.5,317,312.6
XS GIS Cut Line= 6
      3191400.55     13881382.92      3190463.51     13881919.34
      3189682.27     13882166.05      3189081.29     13881995.08
      3187241.29     13882798.41      3186799.42     13883069.16
BEGIN DESCRIPTION:
Cross Section 8530
Located At: 8TH XS US HWY-90
END DESCRIPTION:
#Sta/Elev= 30
  2667.3   45.69  2709.5   42.29  2757.3   40.06  2947.3   40.24  3067.3   42.26
  3272.3    40.5  3422.3   41.12  3452.3   39.47  3482.3   41.03    3747   42.52
    4092    42.5    4167    41.5    4202   38.09    4262   43.95  4569.5   44.89
    4848   44.89  4949.4   43.19  4982.2   42.24  4993.6    36.6  4998.7   36.06
  5006.2   36.45  5021.2   43.25  5035.8   43.55  5056.6   51.41  5071.9   46.76
  5081.9   47.21  5116.9   43.19  5204.5   43.06  7204.2   43.02  7722.4   44.77
#Mann= 8 , 1 , 0
 2667.30     0.2       0  2709.5    0.99       0  4569.5    0.12       0
    4848     0.1       0  4949.4    0.12       0  4982.2    0.04       0
  5021.2    0.12       0  5204.5     0.2       0
#XS Ineff= 2 , 0
       0    4865   44.93  5056.6       0    51.4
Bank Sta=4982.20,5021.20
Exp/Cntr=0.3,0.1

Type RM Length L Ch R = 1 ,8213.0,526.7,434,365.3
XS GIS Cut Line= 6
      3191172.10     13881263.58      3190155.13     13881775.43
      3189561.79     13881838.60      3189348.56     13881759.32
      3187210.21     13882763.59      3186791.23     13883017.60
BEGIN DESCRIPTION:
Cross Section 8213
Located At: 7TH XS US HWY-90
END DESCRIPTION:
#Sta/Elev= 30
  3110.1   45.69  3190.1   39.65  3465.1   42.21  3510.1   40.95  3645.3   41.14
  3880.1   41.76  3975.1   39.32  4000.1   40.61  4035.1   39.66  4133.6    41.9
    4959    42.5  4970.3   41.83  4976.5   44.11  4976.6    42.4  4993.1   36.49
  5000.1   35.92  5005.1   36.58  5020.8    43.1  5035.9   43.83  5050.2   49.96
  5072.8   44.59  5112.8    45.1  5162.8   42.34  5237.3   41.75  5317.8    42.9
  6497.8   43.85  7417.8   44.13  7450.2   42.79  7485.2   44.41  7925.2   44.83
#Mann= 7 , 1 , 0
 3110.10     0.2       0  3645.3    0.12       0  4133.6     0.1       0
    4959    0.12       0  4976.5    0.04       0  5020.8    0.12       0
  5237.3     0.2       0
#XS Ineff= 2 , 0
       0    4250    44.1    5050       0      50
Bank Sta=4976.50,5020.80
Exp/Cntr=0.3,0.1

Type RM Length L Ch R = 1 ,7779.0,866.3,767,724.6
XS GIS Cut Line= 6
      3190552.61     13880904.13      3189947.91     13881237.61
      3189688.96     13881387.96      3189525.06     13881444.97
      3187206.28     13882727.87      3186777.12     13882983.38
BEGIN DESCRIPTION:
Cross Section 7779-Interpolated
END DESCRIPTION:
#Sta/Elev= 30
  3936.9    44.9  3978.8   42.42  4021.9    40.3  4116.9    41.5  4271.9    40.7
  4640.6    42.8  4670.6    40.4  4790.6    41.6  4820.6    38.3  4846.7   42.31
  4875.6    43.4    4940    42.9    4970    40.8  4977.6   42.43  4992.5   36.71
    4999   35.63    5007   36.23  5021.8   42.74    5030    42.1  5063.5    45.6
  5098.5    47.2  5130.3   44.35  5153.5    42.5  5203.5    41.1  5268.5    41.2
  5308.5    42.6  7758.5    43.3  7778.5    44.5  8213.5      44  8249.9      45
#Mann= 6 , 1 , 0
 3936.90     0.2       0  3978.8    0.12       0  4846.7    0.12       0
  4977.6    0.04       0  5021.8    0.12       0  5130.3     0.2       0
#XS Ineff= 2 , 0
       0                    5135       0    47.2
Bank Sta=4977.60,5021.80
Exp/Cntr=0.3,0.1

Type RM Length L Ch R = 1 ,7012.0,1053.1,983,979
XS GIS Cut Line= 5
      3189452.94     13880348.89      3189279.20     13880642.32
      3188927.18     13881084.22      3187182.60     13882640.46
      3187073.23     13882719.58
BEGIN DESCRIPTION:
Cross Section 7012
Located At: 6TH XS US HWY-90
END DESCRIPTION:
#Sta/Elev= 30
  4179.3    45.1  4201.3   44.19  4234.3    41.8  4319.3    41.2  4409.3    41.6
  4439.3      44  4462.8   44.78  4494.3    43.1  4567.8   42.35  4595.3    41.8
  4977.6   41.93  4992.5   36.21    4999   35.13    5007   35.73  5021.8   42.24
  5038.2   43.59  5051.8   49.41  5066.8    49.5  5085.3    44.2  5140.3    41.3
  5190.3    40.7    5231   41.74  5245.3    42.1  5355.3    41.8  5400.3    42.7
  6300.3    43.5  6330.3    43.1  6845.3      44  7528.1    44.1  7558.1    44.8
#Mann= 7 , 1 , 0
 4179.30     0.1       0  4201.3    0.12       0  4462.8    0.13       0
  4567.8    0.12       0  4977.6    0.04       0  5021.8    0.12       0
    5231     0.2       0
#XS Ineff= 2 , 0
       0    4453   44.95    5060       0    49.5
Bank Sta=4977.60,5021.80
Exp/Cntr=0.3,0.1

Type RM Length L Ch R = 1 ,6029.0,863.3,868,862.1
XS GIS Cut Line= 5
      3188476.36     13879827.35      3188299.57     13880194.89
      3188139.44     13880515.16      3188070.11     13880616.83
      3186891.74     13882517.15
BEGIN DESCRIPTION:
Cross Section 6029
Located At: 5TH XS US HWY-90
END DESCRIPTION:
#Sta/Elev= 30
  4184.9    45.2  4199.9    44.9  4204.9   44.67  4214.9    44.2  4215.6   44.19
  4229.9    43.9  4264.9      42  4279.9    41.8  4336.2   41.85  4879.4   42.34
  4977.5   41.61  4993.2   34.89  4998.2   34.42  5002.9   34.86  5022.5   42.58
  5036.9   43.49  5050.7   48.89  5055.8    46.4  5060.8    46.9  5073.9    47.8
  5078.9    47.6  5108.9    43.7  5128.9    42.5  5183.9    41.6  5201.8   41.69
  5223.9    41.8  6123.9    43.3  6288.9    43.2  7308.9    44.2  7309.9    44.5
#Mann= 7 , 1 , 0
 4184.90     0.1       0  4204.9    0.12       0  4215.6    0.13       0
  4336.2    0.12       0  4977.5    0.04       0  5022.5    0.12       0
  5201.8     0.2       0
#XS Ineff= 2 , 0
       0                    5050       0    48.9
Bank Sta=4977.50,5022.50
Exp/Cntr=0.3,0.1

Type RM Length L Ch R = 1 ,5161.0,1121.6,1161,1167.2
XS GIS Cut Line= 5
      3187736.67     13879446.39      3187498.91     13879869.92
      3187291.68     13880246.70      3186388.48     13881628.98
      3186019.14     13882277.47
BEGIN DESCRIPTION:
Cross Section 5161
Located At: 4TH XS US HWY-90
END DESCRIPTION:
#Sta/Elev= 30
  4196.3    45.1  4236.3    41.8  4256.3    40.8  4276.3    40.6  4321.3    41.6
  4451.3    41.8    4817    41.6    4827    41.8  4978.6   41.22  4994.9   34.04
    4997   33.91  4999.9   33.41  5004.9   33.96  5024.5   41.57  5044.4   42.84
  5071.8   48.84    5072    45.3    5092    44.8    5112    41.6    5127    40.7
    5172      40    5197      41    5223   41.05    6602    43.5    6757    43.7
  6773.3    43.3  7063.3    43.8  7103.3    44.8  7138.3    44.4  7509.5    44.8
#Mann= 4 , 1 , 0
 4196.30    0.12       0  4978.6    0.04       0  5024.5    0.12       0
    5223     0.2       0
#XS Ineff= 2 , 0
       0                    5072       0    48.8
Bank Sta=4978.60,5024.50
Exp/Cntr=0.3,0.1

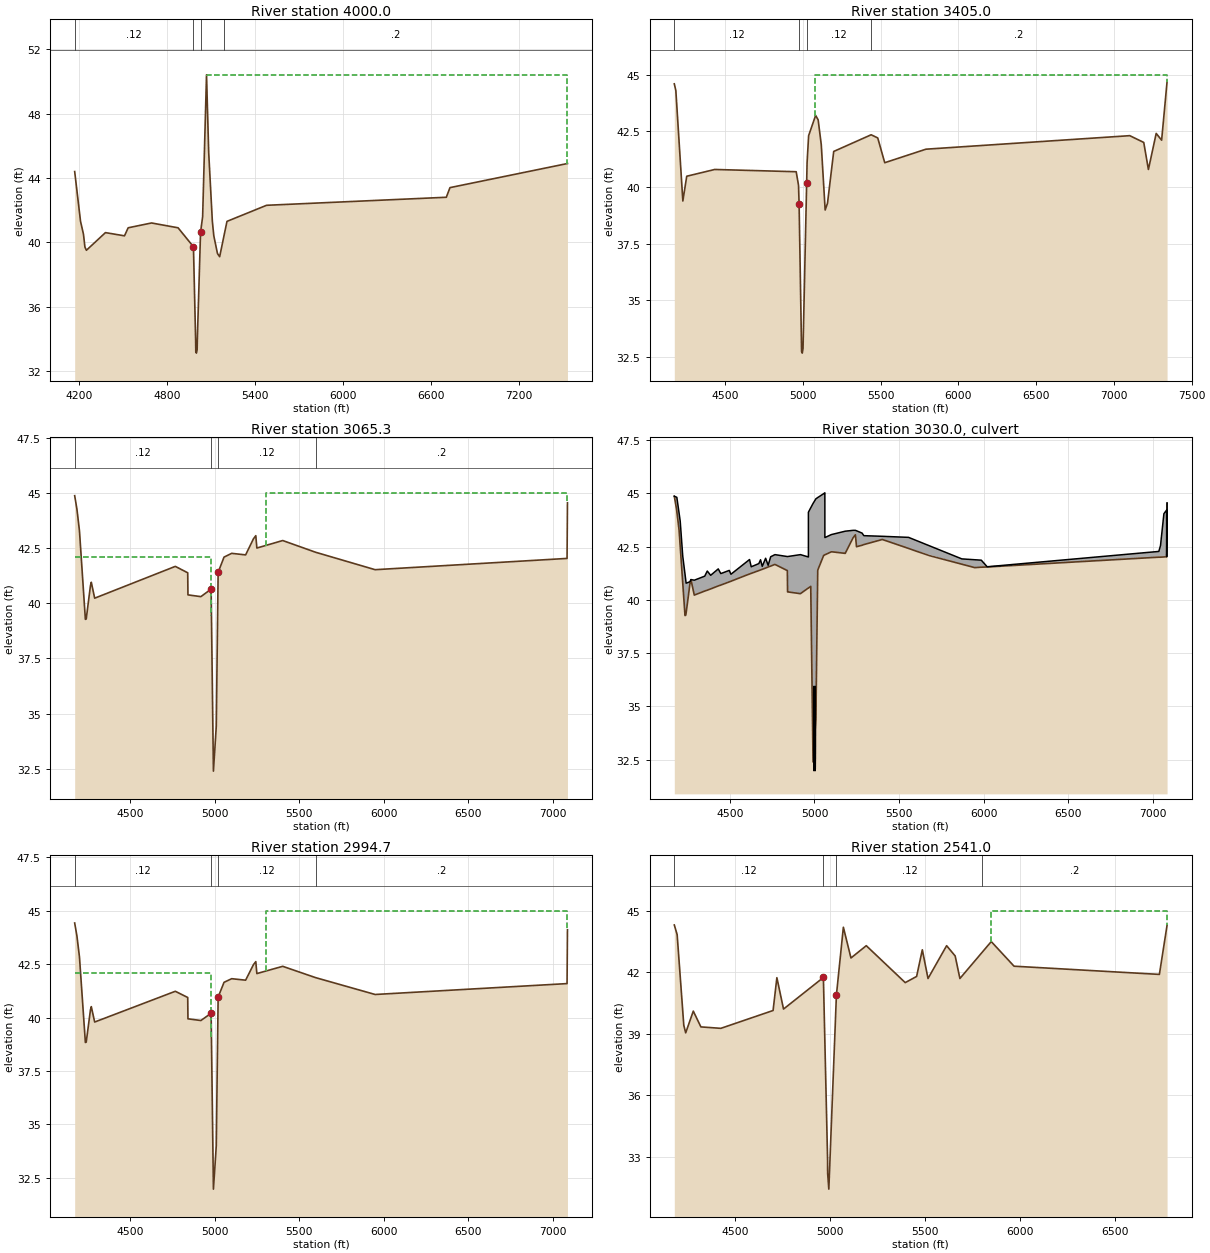
Type RM Length L Ch R = 1 ,4000.0,619.2,595,593.6
XS GIS Cut Line= 5
      3186816.12     13878936.53      3186495.73     13879351.84
      3186238.31     13879720.81      3185741.24     13880681.78
      3185649.80     13881985.44
BEGIN DESCRIPTION:
Cross Section 4000
Located At: 3RD XS US HWY-90
END DESCRIPTION:
#Sta/Elev= 30
  4168.7    44.4  4208.7    41.3  4228.7    40.5  4238.7    39.7  4248.7    39.5
  4378.7    40.6  4508.7    40.4  4533.7    40.9  4693.3    41.2  4874.3    40.9
  4979.3   39.72  4994.4   33.83  4995.3   33.17  4999.5    33.1  5004.5   33.31
  5005.7   33.92  5027.8   40.63    5042   41.59  5068.5   50.42  5083.3    45.6
  5108.3    41.3  5118.3    40.4  5143.2    39.3  5158.2    39.1  5187.2   40.38
  5208.2    41.3  5478.2    42.3  6705.1    42.8  6730.1    43.4  7531.9    44.9
#Mann= 4 , 1 , 0
 4168.70    0.12       0  4979.3    0.04       0  5027.8    0.12       0
  5187.2     0.2       0
#XS Ineff= 2 , 0
       0                  5068.7       0    50.4
Bank Sta=4979.30,5027.80
Exp/Cntr=0.3,0.1

Type RM Length L Ch R = 1 ,3405.0,329.7,339.7,310.4
XS GIS Cut Line= 6
      3186227.68     13878614.04      3185831.65     13879267.07
      3185751.58     13879389.52      3185575.28     13879642.20
      3185169.54     13880137.79      3184017.44     13880761.31
BEGIN DESCRIPTION:
Cross Section 3405
END DESCRIPTION:
#Sta/Elev= 30
  4173.2    44.6  4183.2    44.3  4228.2    39.4  4253.2    40.5  4433.2    40.8
    4957    40.7    4972    40.1 4975.75   39.27 4991.75   32.72 4995.95   32.65
 5000.95   32.86 5024.25   40.18    5027    41.1    5037    42.3    5082    43.2
  5098.3      43  5118.3    41.9  5143.3      39  5158.3    39.3  5198.3    41.6
  5439.1   42.34  5481.4    42.2  5526.4    41.1  5791.4    41.7  7101.9    42.3
  7191.9      42  7221.9    40.8  7271.9    42.4  7306.9    42.1  7341.9    44.7
#Mann= 4 , 1 , 0
 4173.20    0.12       0 4975.75    0.04       0 5024.25    0.12       0
  5439.1     0.2       0
#XS Ineff= 2 , 0
       0                    5080       0      45
Bank Sta=4975.75,5024.25
Exp/Cntr=0.5,0.3

Type RM Length L Ch R = 1 ,3065.3,70.6,70.6,70.6
XS GIS Cut Line= 4
      3185897.17     13878430.63      3185481.17     13879189.74
      3185231.32     13879645.60      3184003.70     13880556.64
BEGIN DESCRIPTION:
Upstream Section of Bridge/Culvert/Weir
END DESCRIPTION:
#Sta/Elev= 27
  4171.1   44.87  4184.4   44.26  4199.4   43.28  4234.4   39.27  4239.4   39.29
  4264.4    40.8  4269.4   40.95  4289.4   40.23  4766.3   41.67  4839.6   41.38
    4841   40.38  4917.4    40.3    4978   40.64  4991.6    32.4  5008.5   34.43
  5019.5    41.4  5054.4   42.09  5099.6   42.26    5182   42.19  5228.5   42.92
  5242.2   43.06  5248.5    42.5  5401.4   42.84  5595.7   42.31  5947.9   41.52
  7082.9   42.03  7085.3   44.55
#Mann= 4 , 1 , 0
 4171.10    0.12       0    4978    0.04       0  5019.5    0.12       0
  5595.7     0.2       0
#XS Ineff= 2 , 0
       0    4980    42.1    5300       0      45
Bank Sta=4978.00,5019.50
Exp/Cntr=0.5,0.3

Type RM Length L Ch R = 2 ,3030.0,,,
BEGIN DESCRIPTION:
ACCESS ROAD
Structure ID: N17-3
END DESCRIPTION:
Bridge Culvert--1,0,-1,-1, 0
Deck Dist Width WeirC Skew NumUp NumDn MinLoCord MaxHiCord MaxSubmerge Is_Ogee
10,50.6,2.6,, 58, 58,,,0.95,0,1,1,,
  4171.1  4186.1  4199.4  4206.1  4221.1  4234.4  4239.4  4241.1  4264.4  4269.4
  4289.4  4351.1  4366.1  4386.1  4431.1  4446.1  4496.1  4506.1  4616.1  4626.1
  4671.1  4681.1  4691.1  4711.1  4726.1  4741.1  4766.3  4839.6    4841  4917.4
 4964.09  4964.2    4978  4991.6  5008.5  5019.5  5054.4  5061.5 5061.61  5099.6
    5182  5228.5  5242.2  5248.5  5281.7  5291.7  5401.4  5556.5  5871.5  5947.9
  5986.5  6021.5  7036.5  7046.5  7066.5  7082.5  7082.9  7085.3
   44.86   44.81   44.07   43.69   42.05   41.21   40.89   40.78   40.85   40.95
   40.92   41.11   41.35   41.15   41.45   41.23   41.38    41.2   41.89   41.55
    41.7   41.88   41.57   41.95   41.62   42.02   42.12   42.03   42.03   42.12
   42.01   44.11   44.32   44.52   44.74    44.8   44.98   45.02   42.92   43.06
   43.22   43.26   43.26   43.24   43.13   43.01   42.98   42.93   41.92   41.88
   41.86   41.55   42.27   42.55   44.04   44.21   42.02   44.54
   44.86   44.14   43.27    42.5   40.78   39.26   39.28   39.38   40.79   40.94
   40.22   40.41   40.45   40.51   40.65   40.69   40.84   40.87   41.21   41.24
   41.37    41.4   41.43   41.49   41.54   41.58   41.66   41.37   40.37   40.29
   40.55   40.55   40.63   32.39   34.42   41.39   42.08   42.11   42.11   42.25
   42.18   42.91   43.05   42.49   42.56   42.59   42.83   42.41   41.67   41.51
   41.53   41.54      42      42   42.01   42.02   42.02   44.54
  4171.1  4186.1  4199.4  4206.1  4221.1  4234.4  4239.4  4241.1  4264.4  4269.4
  4289.4  4351.1  4366.1  4386.1  4431.1  4446.1  4496.1  4506.1  4616.1  4626.1
  4671.1  4681.1  4691.1  4711.1  4726.1  4741.1  4766.3  4839.6    4841  4917.4
 4964.09  4964.2    4978  4991.6  5008.5  5019.5  5054.4  5061.5 5061.61  5099.6
    5182  5228.5  5242.2  5248.5  5281.7  5291.7  5401.4  5556.5  5871.5  5947.9
  5986.5  6021.5  7036.5  7046.5  7066.5  7082.5  7082.9  7085.3
   44.86   44.81   44.07   43.69   42.05   41.21   40.89   40.78   40.85   40.95
   40.92   41.11   41.35   41.15   41.45   41.23   41.38    41.2   41.89   41.55
    41.7   41.88   41.57   41.95   41.62   42.02   42.12   42.03   42.03   42.12
   42.01   44.11   44.32   44.52   44.74    44.8   44.98   45.02   42.92   43.06
   43.22   43.26   43.26   43.24   43.13   43.01   42.98   42.93   41.92   41.88
   41.86   41.55   42.27   42.55   44.04   44.21   42.02   44.54
   44.44   43.72   42.85   42.08   40.36   38.84   38.86   38.96   40.37   40.52
    39.8   39.99   40.03   40.09   40.23   40.27   40.42   40.45   40.79   40.82
   40.95   40.98   41.01   41.07   41.12   41.16   41.24   40.95   39.95   39.87
   40.13   40.13   40.21   31.97      34   40.97   41.66   41.69   41.69   41.83
   41.76   42.49   42.63   42.07   42.14   42.17   42.41   41.99   41.25   41.09
   41.11   41.12   41.58   41.58   41.59    41.6    41.6   44.12
BR Coef= 1 , 0 , 0 ,1.25, 0 ,,,0.8,-1,2,0,
Wspro=,,,, 1 ,,,, 0 ,,,, 0 ,,,,-1 ,-1 ,-1 , 0 , 0 , 0 , 0 , 0
Culvert=1,4.0,,50.6,0.015,0.2,1.0,1,3,31.96,4996.70,31.97,4996.70,Culvert #1  ,0,10
Culvert=1,4.0,,50.6,0.015,0.2,1.0,1,3,31.96,5004.50,31.97,5004.50,Culvert #2  ,0,10
BC Design=,, 0 ,, 0 ,,,,,,
BR U #Sta/Elev= 72
  4171.1   44.86  4184.4   44.25  4186.1   44.14  4199.4   43.27  4206.1    42.5
  4221.1   40.78  4234.4   39.26  4239.4   39.28  4241.1   39.38  4264.4   40.79
  4269.4   40.94  4289.4   40.22  4351.1   40.41  4366.1   40.45  4386.1   40.51
  4431.1   40.65  4446.1   40.69  4496.1   40.84  4506.1   40.87  4586.1   41.12
  4616.1   41.21  4626.1   41.24  4671.1   41.37  4681.1    41.4  4691.1   41.43
  4711.1   41.49  4726.1   41.54  4741.1   41.58  4765.6   41.66  4766.3   41.66
  4839.6   41.37    4841   40.37  4842.9   40.37  4914.5   40.29  4917.4   40.29
  4963.4   40.55 4964.09   40.55  4964.2   40.55 4964.31   40.55    4978   40.63
  4991.6   32.39  5004.5   33.94  5008.5   34.42  5019.5   41.39  5054.4   42.08
 5061.39   42.11  5061.5   42.11 5061.61   42.11  5099.6   42.25  5104.6   42.25
  5180.8   42.18    5182   42.18  5228.5   42.91  5240.1   43.03  5242.2   43.05
  5248.5   42.49  5281.7   42.56  5291.7   42.59  5401.4   42.83  5556.5   42.41
  5595.7    42.3  5681.4   42.07  5871.5   41.67  5947.9   41.51  5986.5   41.53
  6021.5   41.54  7036.5      42  7046.5      42  7066.5   42.01  7082.5   42.02
  7082.9   42.02  7085.3   44.54
BR U #Mann= 4
 4171.10    0.12    4978   0.015  5019.5    0.12  5595.7     0.2
BR U Banks=4978.00,5019.50
BR D #Sta/Elev= 72
  4171.1   44.44  4184.4   43.83  4186.1   43.72  4199.4   42.85  4206.1   42.08
  4221.1   40.36  4234.4   38.84  4239.4   38.86  4241.1   38.96  4264.4   40.37
  4269.4   40.52  4289.4    39.8  4351.1   39.99  4366.1   40.03  4386.1   40.09
  4431.1   40.23  4446.1   40.27  4496.1   40.42  4506.1   40.45  4586.1    40.7
  4616.1   40.79  4626.1   40.82  4671.1   40.95  4681.1   40.98  4691.1   41.01
  4711.1   41.07  4726.1   41.12  4741.1   41.16  4765.6   41.24  4766.3   41.24
  4839.6   40.95    4841   39.95  4842.9   39.95  4914.5   39.87  4917.4   39.87
  4963.4   40.13 4964.09   40.13  4964.2   40.13 4964.31   40.13    4978   40.21
  4991.6   31.97  5004.5   33.52  5008.5      34  5019.5   40.97  5054.4   41.66
 5061.39   41.69  5061.5   41.69 5061.61   41.69  5099.6   41.83  5104.6   41.83
  5180.8   41.76    5182   41.76  5228.5   42.49  5240.1   42.61  5242.2   42.63
  5248.5   42.07  5281.7   42.14  5291.7   42.17  5401.4   42.41  5556.5   41.99
  5595.7   41.88  5681.4   41.65  5871.5   41.25  5947.9   41.09  5986.5   41.11
  6021.5   41.12  7036.5   41.58  7046.5   41.58  7066.5   41.59  7082.5    41.6
  7082.9    41.6  7085.3   44.12
BR D #Mann= 4
 4171.10    0.12    4978   0.015  5019.5    0.12  5595.7     0.2
BR D Banks=4978.00,5019.50

Type RM Length L Ch R = 1 ,2994.7,453.7,453.7,453.7
XS GIS Cut Line= 4
      3185835.15     13878396.89      3185419.15     13879156.00
      3185169.30     13879611.86      3183941.68     13880522.89
BEGIN DESCRIPTION:
Downstream Section of Bridge/Culvert/Weir
END DESCRIPTION:
#Sta/Elev= 27
  4171.1   44.43  4184.4   43.82  4199.4   42.84  4234.4   38.83  4239.4   38.85
  4264.4   40.36  4269.4   40.51  4289.4   39.79  4766.3   41.23  4839.6   40.94
    4841   39.94  4917.4   39.86    4978    40.2  4991.6   31.96  5008.5   33.99
  5019.5   40.96  5054.4   41.65  5099.6   41.82    5182   41.75  5228.5   42.48
  5242.2   42.62  5248.5   42.06  5401.4    42.4  5595.7   41.87  5947.9   41.08
  7082.9   41.59  7085.3   44.11
#Mann= 4 , 1 , 0
 4171.10    0.12       0    4978    0.04       0  5019.5    0.12       0
  5595.7     0.2       0
#XS Ineff= 2 , 0
       0    4980    42.1    5300       0      45
Bank Sta=4978.00,5019.50
Exp/Cntr=0.5,0.3

Type RM Length L Ch R = 1 ,2541.0,529.9,506,505.1
XS GIS Cut Line= 4
      3185457.64     13878203.35      3184955.63     13879045.71
      3184823.76     13879479.01      3183925.77     13880214.06
BEGIN DESCRIPTION:
Cross Section 2541
END DESCRIPTION:
#Sta/Elev= 30
  4180.9   44.31  4195.9   43.84  4230.9   39.42  4240.9   39.05  4280.9   40.11
  4320.9   39.34  4425.9   39.27  4700.9   40.14  4720.9   41.74  4755.9   40.21
 4965.75   41.75 4987.85   32.86 4988.15   32.21 4994.35   31.43 5034.25   40.89
  5070.9    44.2  5110.9    42.7  5191.5    43.3  5396.5    41.5  5456.5    41.8
  5486.5    43.1  5516.5    41.7  5614.4    43.3  5659.4    42.8  5684.4    41.7
  5802.6   42.99  5849.4    43.5  5969.4    42.3  6734.4    41.9  6774.9    44.3
#Mann= 4 , 1 , 0
 4180.90    0.12       0 4965.75    0.04       0 5034.25    0.12       0
  5802.6     0.2       0
#XS Ineff= 2 , 0
       0                    5850       0      45
Bank Sta=4965.75,5034.25
Exp/Cntr=0.3,0.1

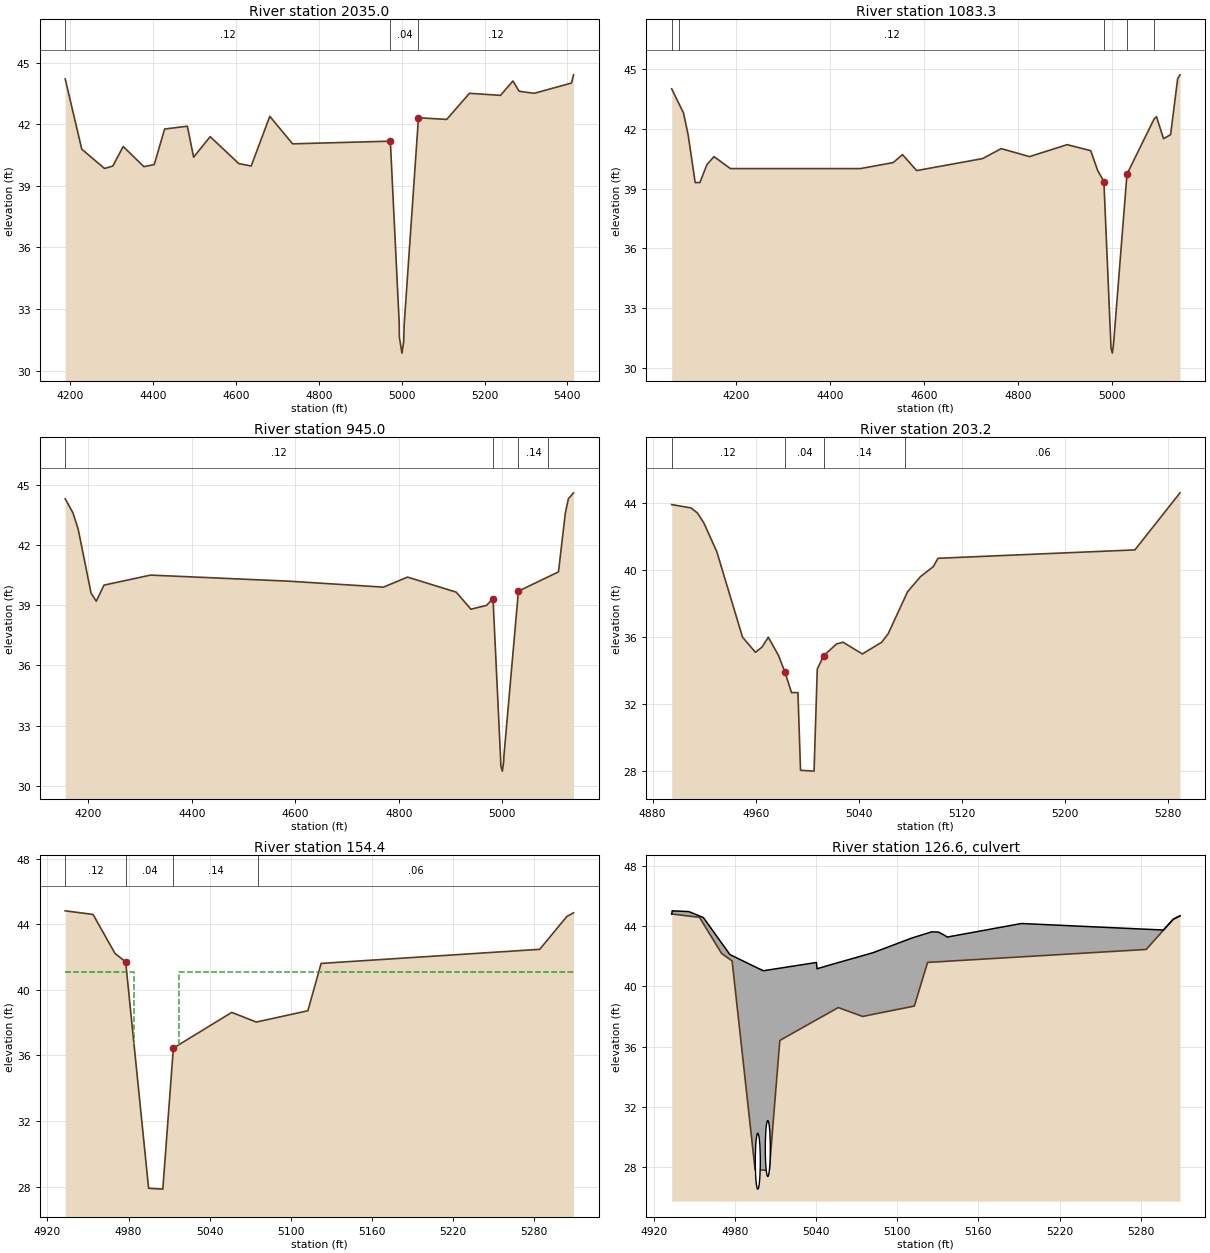
Type RM Length L Ch R = 1 ,2035.0,754.9,951.7,983.9
XS GIS Cut Line= 6
      3184988.35     13877960.99      3184776.19     13878256.82
      3184674.46     13878524.34      3184512.44     13878806.92
      3184470.99     13878957.63      3184429.01     13879042.86
BEGIN DESCRIPTION:
Cross Section 2035
Located At: 2ND XS US HWY-90
END DESCRIPTION:
#Sta/Elev= 30
  4187.5    44.2  4227.5   40.78  4282.5   39.84  4302.5   39.96  4327.5   40.91
  4377.5   39.93  4402.5   40.03  4427.5   41.76  4482.5    41.9  4497.5   40.39
  4537.5   41.39  4606.5   40.08  4636.5   39.96  4681.5   42.38  4736.5   41.04
  4972.5   41.17    4994   32.28  4994.3   31.63  5000.5   30.85  5004.8   31.41
  5005.9   32.23  5040.4   42.31  5108.6   42.23  5163.5    43.5  5238.5    43.4
  5268.5    44.1  5283.5    43.6  5319.8    43.5  5409.8      44  5414.8    44.4
#Mann= 3 , 1 , 0
 4187.50    0.12       0  4972.5    0.04       0  5040.4    0.12       0
Bank Sta=4972.50,5040.40
Exp/Cntr=0.3,0.1

Type RM Length L Ch R = 1 ,1083.3,89.9,138.3,154.2
XS GIS Cut Line= 4
      3184553.78     13877723.40      3184233.70     13877965.13
      3183920.39     13878142.78      3183624.90     13878265.66
BEGIN DESCRIPTION:
Cross Section 1083.3 - Interpolated
END DESCRIPTION:
#Sta/Elev= 30
  4062.8      44  4079.4    43.2  4087.8    42.8  4097.8    41.7  4112.8    39.3
  4122.8    39.3  4137.8    40.2  4152.8    40.6  4187.8      40  4463.9      40
  4533.9    40.3  4553.9    40.7  4583.9    39.9  4723.9    40.5  4763.9      41
  4824.1    40.6  4904.1    41.2  4954.1    40.9  4969.1    39.9  4982.2   39.35
  4997.4      31  5000.2   30.75  5002.8   31.22  5031.3   39.72  5089.3    42.5
  5094.1    42.6  5109.1    41.5  5124.1    41.7  5139.1    44.5  5144.1    44.7
#Mann= 5 , 1 , 0
 4062.80     0.2       0  4079.4    0.12       0  4982.2    0.04       0
  5031.3    0.14       0  5089.3    0.04       0
Bank Sta=4982.20,5031.30
Exp/Cntr=0.3,0.1

Type RM Length L Ch R = 1 ,945.0,755.9,741.8,723.9
XS GIS Cut Line= 4
      3184448.75     13877663.34      3183917.12     13878057.13
      3183608.16     13878091.04      3183600.35     13878097.29
BEGIN DESCRIPTION:
Cross Section 945
Located At: 1ST XS US HWY-90
END DESCRIPTION:
#Sta/Elev= 26
  4155.4    44.3  4170.4    43.6  4180.4    42.8  4205.4    39.6  4215.4    39.2
  4230.4      40  4320.4    40.5  4585.4    40.2  4770.4    39.9    4817    40.4
  4911.1   39.65  4939.5    38.8  4969.6   38.99  4982.2   39.33  4996.7   31.44
  4997.4   30.98  5000.2   30.73  5002.8    31.2  5003.2   31.47  5031.3    39.7
  5089.3   40.42  5108.7   40.66    5122    43.6    5127    44.2  5127.8    44.3
  5137.8    44.6
#Mann= 4 , 1 , 0
 4155.40    0.12       0  4982.2    0.04       0  5031.3    0.14       0
  5089.3    0.04       0
Bank Sta=4982.20,5031.30
Exp/Cntr=0.3,0.1

Type RM Length L Ch R = 1 ,203.2,59.9,48.8,37.7
XS GIS Cut Line= 4
      3183727.69     13877272.75      3183666.60     13877328.89
      3183563.33     13877397.15      3183578.38     13877584.28
BEGIN DESCRIPTION:
Cross Section 203.2 - Interpolated
END DESCRIPTION:
#Sta/Elev= 29
  4894.8    43.9  4909.8    43.7  4914.8    43.4  4919.8    42.8  4929.8    41.1
  4949.8      36  4959.8    35.1  4964.8    35.4  4969.8      36  4977.8    34.9
  4982.8    33.9  4987.8    32.7  4992.8    32.7  4994.8   28.07  5005.3   28.02
  5007.8    34.1  5012.8    34.9  5022.8    35.6  5027.8    35.7  5042.8      35
  5057.8    35.7  5062.8    36.2  5075.6   38.33  5077.8    38.7  5087.8    39.6
  5097.8    40.2  5101.5    40.7  5254.3    41.2  5289.3    44.6
#Mann= 4 , 1 , 0
 4894.80    0.12       0  4982.8    0.04       0  5012.8    0.14       0
  5075.6    0.06       0
Bank Sta=4982.80,5012.80
Exp/Cntr=0.5,0.3

Type RM Length L Ch R = 1 ,154.4,55.6,55.6,55.6
XS GIS Cut Line= 6
      3183674.30     13877235.69      3183648.45     13877280.03
      3183608.93     13877332.37      3183565.13     13877374.03
      3183553.38     13877397.53      3183567.97     13877569.19
BEGIN DESCRIPTION:
Upstream Section of Bridge/Culvert/Weir
END DESCRIPTION:
#Sta/Elev= 15
  4933.1   44.83  4953.7   44.61    4970   42.22  4977.8   41.72  4994.8   27.89
  5005.3   27.84  5013.1   36.45  5056.3   38.63  5074.4   38.04  5075.6   38.06
  5112.6   38.73  5122.4   41.62  5284.1   42.48  5304.1   44.48  5309.1   44.71
#Mann= 4 , 1 , 0
 4933.10    0.12       0  4977.8    0.04       0  5013.1    0.14       0
  5075.6    0.06       0
#XS Ineff= 2 , 0
       0    4984    41.1    5017       0    41.1
Bank Sta=4977.80,5013.10
Exp/Cntr=0.5,0.3

Type RM Length L Ch R = 2 ,126.6,,,
BEGIN DESCRIPTION:
ACCESS ROAD - 30 Degree Skew
Structure ID: N17-1
END DESCRIPTION:
Bridge Culvert--1,0,-1,-1, 0
Deck Dist Width WeirC Skew NumUp NumDn MinLoCord MaxHiCord MaxSubmerge Is_Ogee
10,35.6,3,,31,31,,,0.95,0,1,1,,
  4933.1  4933.5  4945.8  4953.7  4956.6    4970  4976.2  4977.8  4994.8  5000.9
  5005.3  5013.1  5040.2  5040.6    5050  5056.3  5074.4  5075.6  5082.5  5110.5
  5112.6  5122.4  5125.5  5130.5  5135.5  5136.8  5191.8  5284.1  5296.8  5304.1
  5309.1
   44.79      45   44.95   44.66   44.55   42.87    42.1   42.03   41.29   41.03
   41.09    41.2   41.58   41.16   41.41   41.57   42.03   42.06   42.24   43.19
   43.25   43.52   43.61   43.59   43.35   43.26   44.16   43.78   43.73   44.44
   44.67
   44.79   44.79   44.65   44.57   44.14   42.18   41.78   41.68   27.85   27.82
    27.8   36.41   37.78    37.8   38.27   38.59      38   38.02   38.15   38.65
   38.69   41.58    41.6   41.62   41.65   41.66   41.95   42.44   43.71   44.44
   44.67
  4933.1  4933.5  4945.8  4953.7  4956.6    4970  4976.2  4977.8  4994.8  5000.9
  5005.3  5013.1  5040.2  5040.6    5050  5056.3  5074.4  5075.6  5082.5  5110.5
  5112.6  5122.4  5125.5  5130.5  5135.5  5136.8  5191.8  5284.1  5296.8  5304.1
  5309.1
   44.79      45   44.95   44.66   44.55   42.87    42.1   42.03   41.29   41.03
   41.09    41.2   41.58   41.16   41.41   41.57   42.03   42.06   42.24   43.19
   43.25   43.52   43.61   43.59   43.35   43.26   44.16   43.78   43.73   44.44
   44.67
   43.37   43.37   43.23   43.15   42.72   40.76   40.36   40.26   26.43    26.4
   26.38   34.99   36.36   36.38   36.85   37.17   36.58    36.6   36.73   37.23
   37.27   40.16   40.18    40.2   40.23   40.24   40.53   41.02   42.29   43.02
   43.25
BR Coef= 1 , 0 , 0 ,1.25, 0 ,,,0.8,-1,2,0,
Wspro=,,,, 1 ,,,, 0 ,,,, 0 ,,,,-1 ,-1 ,-1 , 0 , 0 , 0 , 0 , 0
Culvert=1,3.7,,35.6,0.015,0.2,1.0,1,3,26.56,4996.80,26.38,4996.80,Culvert #1  ,0,10
Culvert=1,3.7,,35.6,0.015,0.2,1.0,1,3,27.40,5004.20,27.12,5004.20,Culvert #2  ,0,10
BC Design=,, 0 ,, 0 ,,,,,,
BR U #Sta/Elev= 31
  4933.1   44.79  4933.5   44.79  4945.8   44.65  4953.7   44.57  4956.6   44.14
    4970   42.18  4976.2   41.78  4977.8   41.68  4994.8   27.85  5000.9   27.82
  5005.3    27.8  5013.1   36.41  5040.2   37.78  5040.6    37.8    5050   38.27
  5056.3   38.59  5074.4      38  5075.6   38.02  5082.5   38.15  5110.5   38.65
  5112.6   38.69  5122.4   41.58  5125.5    41.6  5130.5   41.62  5135.5   41.65
  5136.8   41.66  5191.8   41.95  5284.1   42.44  5296.8   43.71  5304.1   44.44
  5309.1   44.67
BR U #Mann= 4
 4933.10    0.12  4977.8    0.04  5013.1    0.14  5075.6    0.06
BR U Banks=4977.80,5013.10
BR D #Sta/Elev= 31
  4933.1   43.37  4933.5   43.37  4945.8   43.23  4953.7   43.15  4956.6   42.72
    4970   40.76  4976.2   40.36  4977.8   40.26  4994.8   26.43  5000.9    26.4
  5005.3   26.38  5013.1   34.99  5040.2   36.36  5040.6   36.38    5050   36.85
  5056.3   37.17  5074.4   36.58  5075.6    36.6  5082.5   36.73  5110.5   37.23
  5112.6   37.27  5122.4   40.16  5125.5   40.18  5130.5    40.2  5135.5   40.23
  5136.8   40.24  5191.8   40.53  5284.1   41.02  5296.8   42.29  5304.1   43.02
  5309.1   43.25
BR D #Mann= 4
 4933.10    0.12  4977.8    0.04  5013.1    0.14  5075.6    0.06
BR D Banks=4977.80,5013.10

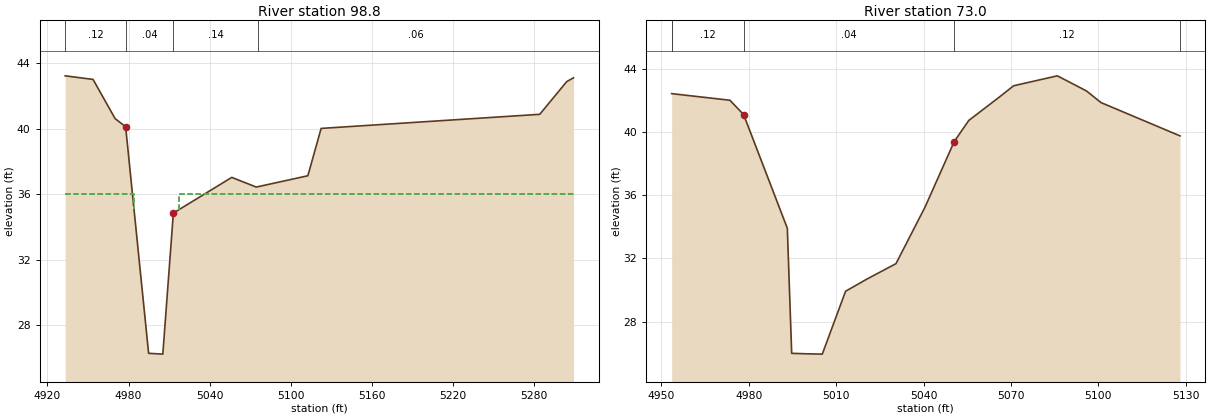
Type RM Length L Ch R = 1 ,98.8,25.8,25.8,25.8
XS GIS Cut Line= 6
      3183633.16     13877198.29      3183607.31     13877242.63
      3183567.79     13877294.97      3183523.99     13877336.63
      3183512.24     13877360.13      3183526.83     13877531.79
BEGIN DESCRIPTION:
Downstream Section of Bridge/Culvert/Weir
END DESCRIPTION:
#Sta/Elev= 15
  4933.1   43.24  4953.7   43.02    4970   40.63  4977.8   40.13  4994.8    26.3
  5005.3   26.25  5013.1   34.86  5056.3   37.04  5074.4   36.45  5075.6   36.47
  5112.6   37.14  5122.4   40.03  5284.1   40.89  5304.1   42.89  5309.1   43.12
#Mann= 4 , 1 , 0
 4933.10    0.12       0  4977.8    0.04       0  5013.1    0.14       0
  5075.6    0.06       0
#XS Ineff= 2 , 0
       0    4984      36    5017       0      36
Bank Sta=4977.80,5013.10
Exp/Cntr=0.5,0.3

Type RM Length L Ch R = 1 ,73.0,0,0,0
XS GIS Cut Line= 5
      3183596.41     13877209.63      3183583.01     13877230.35
      3183559.52     13877265.60      3183528.54     13877298.71
      3183508.24     13877357.46
BEGIN DESCRIPTION:
Cross Section 73-Interpolated
END DESCRIPTION:
#Sta/Elev= 19
  4953.5   42.46  4973.5   42.04  4978.2   41.13  4993.2   33.92  4994.7   25.98
    5000   25.95  5005.2   25.93  5013.2   29.92  5020.5   30.69  5030.5   31.67
  5040.5   35.27  5050.5   39.42  5055.5   40.76  5065.9   42.23  5070.9   42.96
  5085.9   43.59  5095.9   42.63  5100.9   41.89    5128   39.78
#Mann= 5 , 1 , 0
 4953.50     0.2       0  4953.5    0.12       0  4978.2    0.04       0
  5050.5    0.12       0    5128     0.2       0
Bank Sta=4978.20,5050.50
Exp/Cntr=0.3,0.1

Chan Stop Cuts=-1